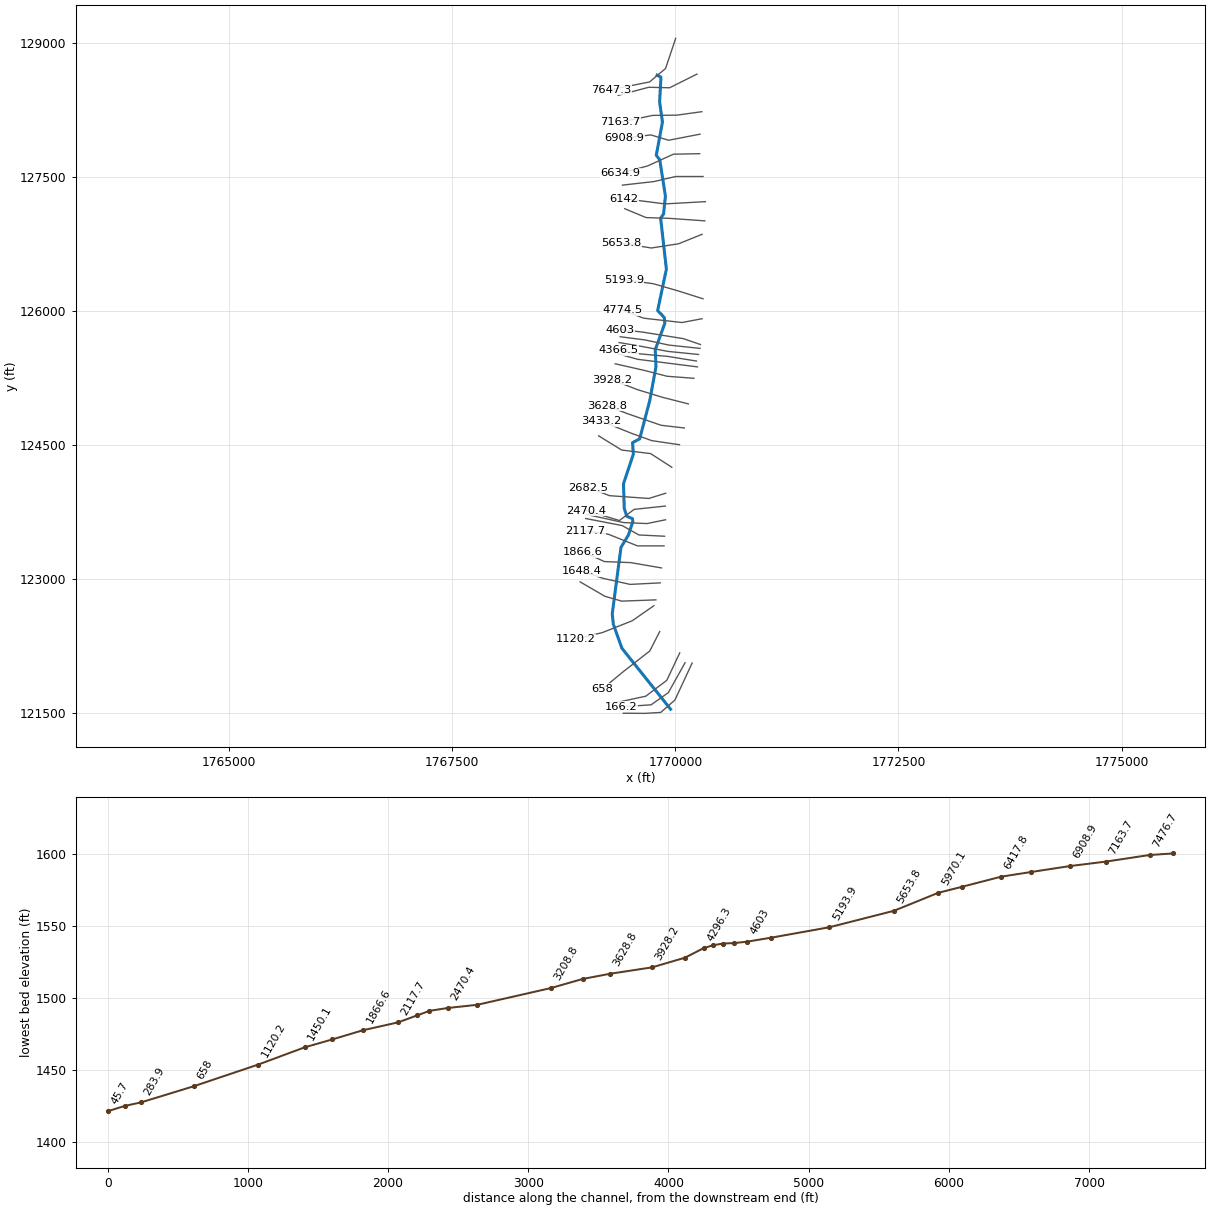
--- Harmon Branch B.prj (project) ---

Proj Title=Harmon Branch B
Current Plan=p01
Default Exp/Contr=0,0
English Units
Geom File=g01
Flow File=f01
Plan File=p01
BEGIN DESCRIPTION:
END DESCRIPTION:
DSS Export Rating Curves= 0
DSS Export Rating Curve Sorted= 0
DSS Export Volume Flow Curves= 0
DXF OffsetX= 0
DXF OffsetY= 0
DXF ScaleX= 0
DXF ScaleY= 0

--- Harmon Branch B.p01 (plan) ---

Plan Title=Floodplain
Program Version=4.00
Geom File=g01
Flow File=f01
K Sum by GR=0
Std Step Tol=0.01
Critical Tol=0.01
Num of Std Step Trials=20
Max Error Tol=0.3
Flow Tol Ratio=0.001
Split Flow NTrial=30
Split Flow Tol=0.02
Split Flow Ratio=0.02
Log Output Level=0
Friction Slope Method=1
Unsteady Friction Slope Method=2
Unsteady Bridges Friction Slope Method=1
Global Log Level=0
CheckData=False
Run HTab=0
Run UNet=0
Run PostProcess=0
UNET Theta=0
UNET Theta Warmup=0
UNET ZTol=0
UNET ZSATol=0
UNET MxIter=0
UNET MaxInSteps=0
UNET DtIC=0
UNET DtMin=0
UNET MaxCRTS=0
UNET WFStab=0
UNET SFStab=0
UNET WFX=0
UNET SFX=0
UNET DSS MLevel=0
UNET DZMax Abort=0
UNET Convert EG Bridges=0
UNET Use Existing IB Tables=0
UNET Froude Limit=0
UNET Froude Power=0
Write IC File=0
Echo Input=False
Echo Output=False
Write Detailed=0

--- Harmon Branch B.f01 (steady flow) ---

Flow Title=NFF Regression Equation
Program Version=4.00
Number of Profiles=1
Profile Names=P100yr
River Rch & RM=Harmon Branch B,Main      ,7647.3
370.7644
River Rch & RM=Harmon Branch B,Main      ,7476.7
652.5910
River Rch & RM=Harmon Branch B,Main      ,5970.1
692.4833
River Rch & RM=Harmon Branch B,Main      ,4774.5
752.5361
River Rch & RM=Harmon Branch B,Main      ,3208.8
834.9752
River Rch & RM=Harmon Branch B,Main      ,283.9
924.9894
Boundary for River Rch & Prof#=Harmon Branch B,Main      ,1
Up Type=0
Dn Type=3
Dn Slope=0.026812

--- Harmon Branch B.g01 (geometry) ---

Geom Title=USGS 10m DEM
Program Version=4.00

River Reach=Harmon Branch B ,Main
Reach XY= 30
     1769796.069      128640.486     1769838.865      128618.514
     1769823.848      128339.938      1769855.82      128116.132
     1769786.394      127743.426     1769825.675      127691.357
     1769888.986      127285.508     1769867.695      127083.884
     1769835.357      127037.792     1769899.668      126467.275
     1769801.924      126004.134     1769875.917      125925.573
     1769882.236       125861.01      1769774.94      125564.451
     1769783.331      125375.801     1769713.315      124994.723
     1769600.412      124566.258     1769520.568      124523.361
     1769529.703      124395.471      1769419.17       124062.96
     1769427.235      123789.753      1769455.71      123699.389
     1769519.654      123671.984     1769524.222      123640.926
     1769474.619      123488.987     1769390.823      123350.326
     1769293.062      122605.145     1769305.897      122487.183
     1769401.813      122219.529     1769946.808      121537.232

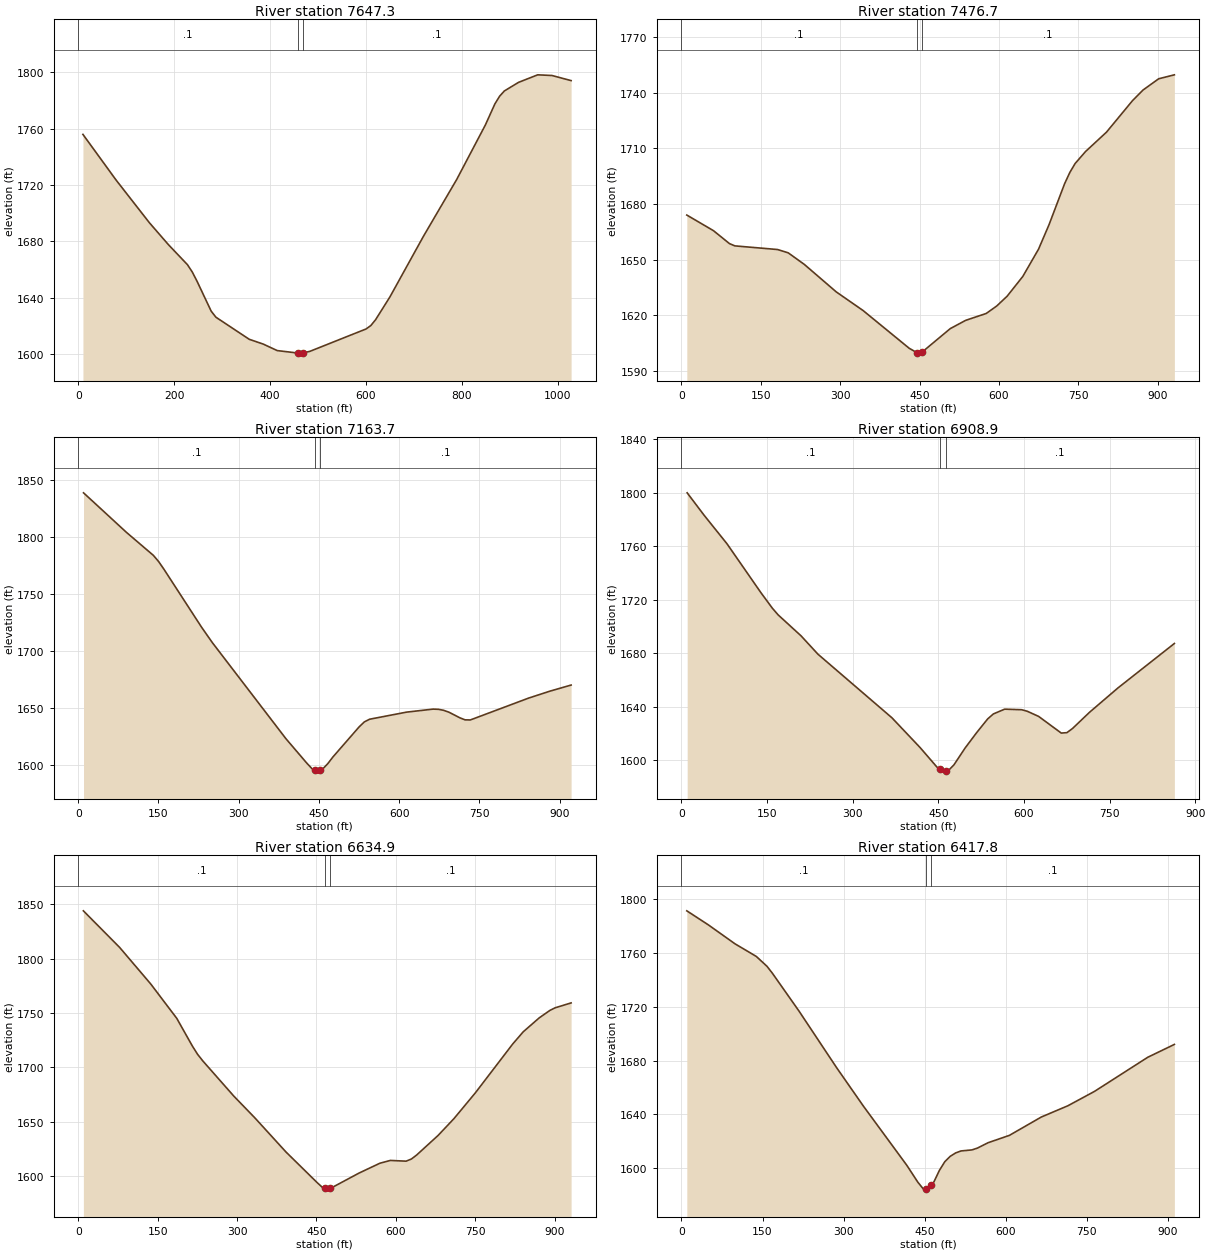
Type RM Length L Ch R = 1 ,7647.3  ,184.5,170.7,156.1
XS GIS Cut Line= 4
     1770003.981      129053.425     1769890.371      128715.436
     1769711.436      128564.903     1769282.559      128479.696
#Sta/Elev= 30
     9.9 1755.98    79.2 1723.47   148.6 1693.18   188.2 1677.64   227.8 1663.45
   237.7 1658.34   247.6 1651.84   277.3 1630.43   287.2 1626.13   356.6 1610.46
   385.8 1607.05     415 1602.43   458.7 1600.66   463.7 1600.63   468.7 1600.77
   483.2 1601.91   600.3  1617.8   610.3 1620.26   620.2 1624.43     650 1640.59
   719.6 1683.47   789.2 1723.97   848.8 1762.57   868.7 1777.57   878.6 1783.07
   888.5 1786.82   918.3 1792.96   958.1 1798.28   987.9  1797.8  1027.7 1794.17
#Mann= 3 , 0 , 0
       0      .1       0   458.7    .045       0   468.7      .1       0
Bank Sta=458.7,468.7
XS Rating Curve= 0 ,0
Exp/Cntr=0.3,0.1

Type RM Length L Ch R = 1 ,7476.7  ,312.5,312.9,313.5
XS GIS Cut Line= 4
     1770242.561      128652.951     1769935.815      128499.578
     1769702.915      128505.258     1769359.246       128414.37
#Sta/Elev= 30
    10.1    1674    60.5 1665.57    90.8 1658.58   100.9 1657.37   181.6  1655.4
   201.7 1653.62     232 1647.41   292.5 1632.54     343 1622.53   430.3 1602.13
   444.7 1599.81   449.7 1599.51   454.7 1600.07     508 1612.75   537.1  1617.2
   575.9 1620.91   595.7 1624.93   615.4 1630.23     645 1640.88   674.7 1655.59
   694.4 1668.69     724 1690.93   733.9 1697.01   743.8 1701.78   763.5 1708.26
     803 1718.69   852.4 1735.76   872.2 1741.46   901.8 1747.53   931.4 1749.65
#Mann= 3 , 0 , 0
       0      .1       0   444.7    .045       0   454.7      .1       0
Bank Sta=444.7,454.7
XS Rating Curve= 0 ,0
Exp/Cntr=0.3,0.1

Type RM Length L Ch R = 1 ,7163.7  ,260.9,254.8,248.7
XS GIS Cut Line= 4
      1770297.27      128231.748      1770018.95      128192.994
     1769745.519      128189.991     1769386.315      128114.543
#Sta/Elev= 30
      10 1838.94    90.3 1804.24   140.5 1784.13   150.5 1778.61   160.6 1771.72
   230.8 1721.01   250.9 1707.53   388.4 1623.33   427.5 1601.86   437.3 1596.96
     442 1595.96     447 1594.91     452 1595.79   456.8 1596.63   466.6 1601.45
   476.3 1607.37   525.2  1633.7   534.9 1638.06   544.7 1640.41     614 1646.65
   663.6 1649.29   673.5  1649.1   683.4 1648.21   693.3 1646.54   713.2 1641.74
   723.1 1639.89     733 1639.77   842.1 1658.95   881.8 1665.02   921.5 1670.38
#Mann= 3 , 0 , 0
       0      .1       0     442    .045       0     452      .1       0
Bank Sta=442,452
XS Rating Curve= 0 ,0
Exp/Cntr=0.3,0.1

Type RM Length L Ch R = 1 ,6908.9  ,258.9,274,289.2
XS GIS Cut Line= 4
     1770276.644      127979.813     1769924.454      127911.647
     1769725.637      127971.293     1769430.252       127937.21
#Sta/Elev= 30
      10 1799.93    39.9 1783.05    79.7 1761.88   139.5  1725.1   159.4 1713.59
   169.4 1708.66   209.3 1693.09   239.2 1679.25   368.6 1631.78     418 1609.51
   447.7 1594.83   452.6 1593.35   457.6 1591.84   462.6 1592.03   467.5 1592.22
   477.3 1596.48   497.1 1609.22   516.9 1620.48   536.6 1630.93   546.5 1634.61
   566.3 1638.18     596 1637.75   605.9  1636.6   625.8 1632.74   665.4  1620.3
   675.3  1620.6   685.2 1623.74     715 1635.86   764.5 1653.96   863.6 1687.28
#Mann= 3 , 0 , 0
       0      .1       0   452.6    .045       0   462.6      .1       0
Bank Sta=452.6,462.6
XS Rating Curve= 0 ,0
Exp/Cntr=0.3,0.1

Type RM Length L Ch R = 1 ,6634.9  ,221.3,217.1,212.9
XS GIS Cut Line= 4
     1770272.503       127761.16     1769978.419      127755.434
     1769691.554      127624.783     1769381.289        127539.3
#Sta/Elev= 30
     9.8 1844.02    78.4 1810.27   137.3 1776.52   186.3 1744.97   215.7 1719.53
   225.5 1711.95   235.3 1705.89   294.1 1673.35   333.5 1653.51   392.6 1621.93
   451.7 1593.64   461.6 1589.24   466.4 1588.51   471.4 1587.75   476.4 1588.39
   530.6 1602.54     570  1611.6   589.7 1614.17   619.4  1613.5   629.5 1615.48
   639.5  1619.2   679.8 1637.13   709.9 1652.67   750.2 1676.34   820.6 1721.21
   840.7  1732.6   870.8 1745.38     891 1752.28     901 1754.71   931.2 1759.23
#Mann= 3 , 0 , 0
       0      .1       0   466.4    .045       0   476.4      .1       0
Bank Sta=466.4,476.4
XS Rating Curve= 0 ,0
Exp/Cntr=0.3,0.1

Type RM Length L Ch R = 1 ,6417.8  ,279.3,275.8,269.4
XS GIS Cut Line= 4
     1770310.727      127505.493     1770003.981      127505.493
      1769759.72      127448.688      1769407.53      127408.925
#Sta/Elev= 30
     9.9 1791.32    49.5 1780.95      99 1766.82   138.5 1757.41   158.3 1750.06
   168.2 1744.95   217.7 1716.68     287 1674.78   336.8 1646.06   417.1 1602.08
   437.2 1589.69   447.2 1584.69   452.2 1584.57   457.2 1584.45   462.2 1587.18
   467.2 1589.91   477.3 1598.43   487.3 1604.88   497.3 1608.84   507.4 1611.39
   517.4 1612.84   537.5 1613.61   547.5 1614.94   567.4 1618.96   606.8 1624.42
   665.8 1638.05     715 1646.42   764.3 1657.12   862.7 1682.45     912 1692.02
#Mann= 3 , 0 , 0
       0      .1       0   452.2    .045       0   462.2      .1       0
Bank Sta=452.2,462.2
XS Rating Curve= 0 ,0
Exp/Cntr=0.3,0.1

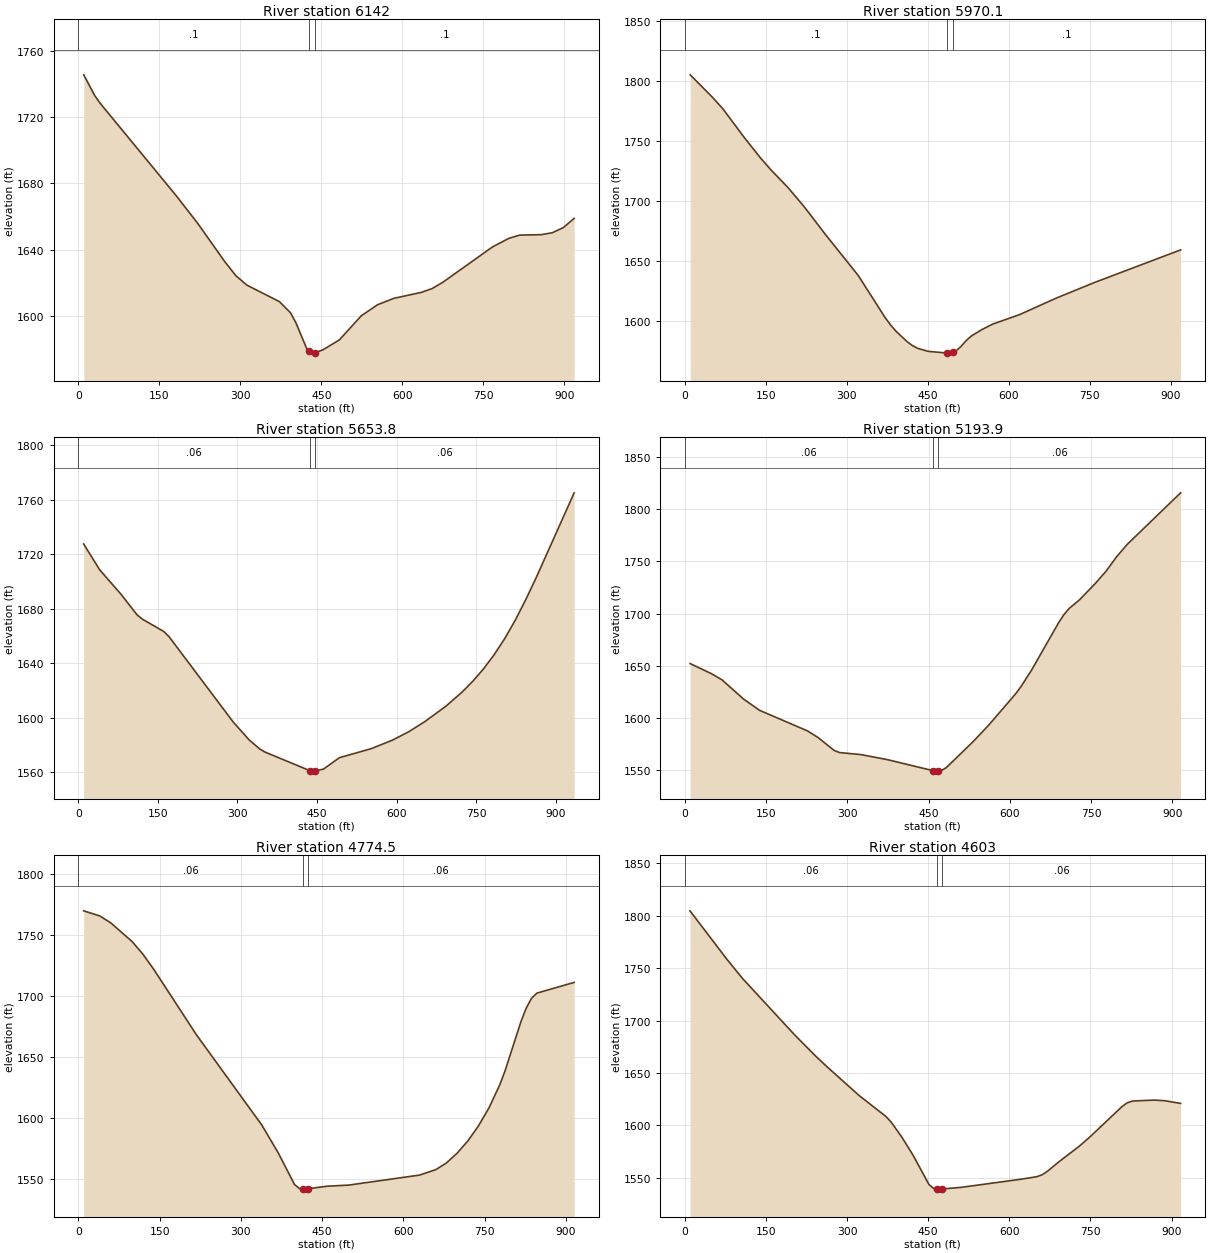
Type RM Length L Ch R = 1 ,6142    ,173.6,171.9,173.1
XS GIS Cut Line= 3
     1770336.829      127223.867     1769884.353      127198.447
     1769422.838      127257.349
#Sta/Elev= 30
    10.1 1745.61    30.2 1733.15    40.3 1728.49   181.3  1672.6   221.6 1655.68
   271.9 1632.47   292.1 1624.19   312.2 1618.57   372.6 1608.58   392.8 1601.95
   402.8 1596.02     423 1580.27     428 1578.88     433  1577.5     438 1577.69
   453.2 1579.53   483.5 1585.48     524 1600.03   554.3 1606.74   584.7 1610.62
   635.2 1614.18   655.5 1616.53   675.7 1620.42   766.7 1641.56   797.1 1646.78
   817.3 1648.79   857.8 1649.06     878 1650.24   898.2 1653.29   918.4 1658.89
#Mann= 3 , 0 , 0
       0      .1       0     428    .045       0     438      .1       0
Bank Sta=428,438
XS Rating Curve= 0 ,0
Exp/Cntr=0.3,0.1

Type RM Length L Ch R = 1 ,5970.1  ,312.5,316.3,320
XS GIS Cut Line= 4
     1770330.609      127008.451     1769930.134      127036.853
     1769671.672      127045.374     1769433.092      127144.782
#Sta/Elev= 30
      10 1804.99    50.2 1786.78    70.3 1776.83   110.4 1752.67   140.5 1735.66
   160.6 1725.35   190.7 1711.37   220.8 1695.36     261 1671.79   321.2 1637.97
   371.4 1602.66   381.4 1596.59   391.4 1591.45   411.4 1582.99   421.4 1579.61
   431.3 1577.25   451.2 1574.72     486 1573.32     491 1573.26     496 1573.92
   500.9 1574.56   510.9 1578.46   520.8  1583.5   530.8 1587.52   550.7 1592.96
   570.6 1597.47   620.3 1605.35   689.9 1619.41   759.5 1632.16   918.5 1659.22
#Mann= 3 , 0 , 0
       0      .1       0     486    .045       0     496      .1       0
Bank Sta=486,496
XS Rating Curve= 0 ,0
Exp/Cntr=0.3,0.1

Type RM Length L Ch R = 1 ,5653.8  ,468.7,459.9,451.1
XS GIS Cut Line= 4
     1770299.366      126857.918     1770038.189       126752.21
     1769731.318      126704.545     1769393.329      126758.509
#Sta/Elev= 30
    10.1 1727.39    40.3 1708.45    80.5 1690.52   110.7 1675.44   120.8 1672.22
     161 1663.25   171.1 1659.35   291.8 1596.86   321.8 1583.74   341.9 1577.02
   351.9 1574.73     437 1560.99     442 1560.75     447 1560.96   462.1 1562.23
   492.1 1570.61   552.2 1577.25   592.3 1583.53   622.5 1589.59   652.7 1596.97
     693 1608.41   723.2  1618.7   743.3  1626.6   763.4 1635.63   783.6 1646.04
   803.7 1657.97   823.8 1671.65     844 1687.05   864.1 1703.63   934.6 1764.95
#Mann= 3 , 0 , 0
       0     .06       0     437    .045       0     447     .06       0
Bank Sta=437,447
XS Rating Curve= 0 ,0
Exp/Cntr=0.3,0.1

Type RM Length L Ch R = 1 ,5193.9  ,415.7,419.4,423.2
XS GIS Cut Line= 4
     1770310.367       126135.63     1770038.064      126221.704
     1769754.039      126304.071     1769423.237      126349.957
#Sta/Elev= 30
     9.8 1652.23    49.2 1642.55    68.9 1636.54   108.3 1618.35   137.9 1607.52
   226.5 1587.82   246.2 1581.39   275.7 1569.13   285.6 1567.09     325 1565.16
   374.3 1560.29     458 1549.81     463 1549.33     468 1549.51   472.9 1549.68
   482.7 1552.66     532 1577.42   561.6 1593.67   610.8 1623.31   620.6 1630.19
   640.2 1646.02   689.4 1690.65   699.2 1698.55     709 1704.66   728.6 1713.18
   758.1 1728.98   777.8 1740.67   797.4 1754.54   817.1 1766.43   915.3 1815.53
#Mann= 3 , 0 , 0
       0     .06       0     458    .045       0     468     .06       0
Bank Sta=458,468
XS Rating Curve= 0 ,0
Exp/Cntr=0.3,0.1

Type RM Length L Ch R = 1 ,4774.5  ,172.6,171.5,170.4
XS GIS Cut Line= 4
     1770299.366      125912.117     1770074.987      125869.514
      1769646.11      125917.798      1769407.53      126008.685
#Sta/Elev= 30
     9.9 1770.17    39.7 1765.95    59.6 1760.41    99.3 1744.97   119.2 1734.64
     139 1722.35   218.5 1668.23   338.8 1594.49   368.9 1571.85     399 1545.85
   409.1 1542.18   414.1  1542.1   419.1 1542.01   424.1 1542.35   459.2 1544.39
   499.4 1545.33   629.9 1553.52     660    1558   679.6 1563.49   699.3 1571.49
   718.9 1581.46   738.5 1593.72   758.2 1608.73   777.8 1627.34   787.6  1638.8
   817.1 1679.35   826.9  1690.5   836.7  1698.5   846.5 1702.69   915.3 1711.48
#Mann= 3 , 0 , 0
       0     .06       0   414.1    .045       0   424.1     .06       0
Bank Sta=414.1,424.1
XS Rating Curve= 0 ,0
Exp/Cntr=0.3,0.1

Type RM Length L Ch R = 1 ,4603    ,92,90.9,89.8
XS GIS Cut Line= 4
     1770281.163      125623.082     1770089.484      125688.844
      1769637.59      125761.584     1769382.895      125790.213
#Sta/Elev= 30
     9.6 1804.73    77.2 1758.94   106.1 1740.58   202.6 1686.65   242.4 1665.92
   262.3 1656.28     322 1628.68   371.8 1608.57   381.8 1603.05   401.7 1588.51
   421.6    1572   451.4 1543.71   461.4 1539.33   466.3 1539.29   471.3 1539.25
   476.3  1539.4   511.1 1540.94   620.6 1548.64   650.4 1551.05   660.4 1552.89
   670.2 1556.16   689.9 1564.61   729.4 1580.23   749.1  1589.1   808.2 1617.93
   818.1 1621.68   827.9 1623.29   867.4 1624.18   887.1 1623.63   916.7 1621.02
#Mann= 3 , 0 , 0
       0     .06       0   466.3    .045       0   476.3     .06       0
Bank Sta=466.3,476.3
XS Rating Curve= 0 ,0
Exp/Cntr=0.3,0.1

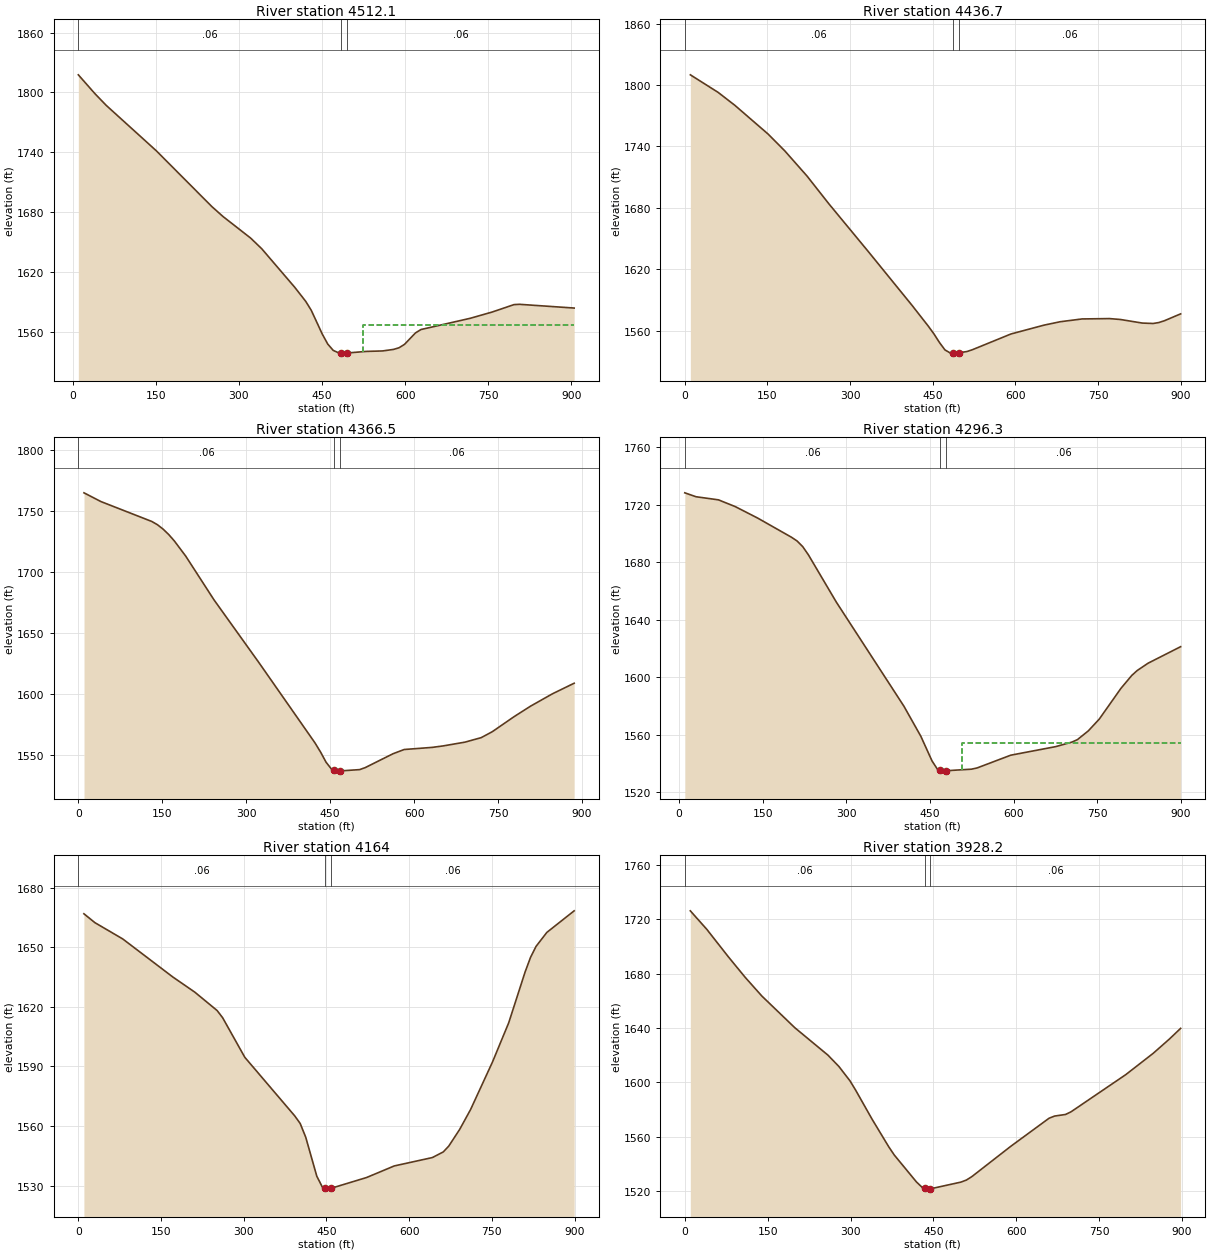
Type RM Length L Ch R = 1 ,4512.1  ,74.8,75.3,75.9
XS GIS Cut Line= 4
     1770276.644      125579.809     1769927.294      125616.732
     1769665.992      125673.537     1769381.968       125710.46
#Sta/Elev= 30
      10 1817.59    40.1 1798.61    60.2 1787.02   150.6 1741.46   250.9 1685.46
     271 1675.49   321.2  1653.7   341.3 1642.95   400.8  1604.3   420.6 1590.21
   430.5  1581.3   450.3 1557.55   460.2 1547.48   470.1 1541.09     480 1538.56
     485 1538.44     490 1538.32     495 1538.43   529.6 1540.04   559.3 1540.51
   579.1 1542.06     589 1543.72   598.9 1547.15   618.7 1558.63   628.6    1562
   717.5 1573.27     757 1579.54   796.5    1587   806.4  1587.3   905.1 1583.55
#Mann= 3 , 0 , 0
      10     .06       0     485    .045       0     495     .06       0
#XS Ineff= 2 , 0
                          524.63         1566.59
Permanent Ineff=
       F       F
Bank Sta=485,495
XS Rating Curve= 0 ,0
Exp/Cntr=0.3,0.1

Type RM Length L Ch R = 1 ,4436.7  ,68.3,70.2,72.2
XS GIS Cut Line= 4
     1770259.602      125511.643     1769918.773      125545.726
     1769634.749       125599.69     1769370.607      125645.134
#Sta/Elev= 30
    10.1 1809.93    60.4 1792.81    90.7  1780.2   151.1 1752.08   181.3 1735.72
   221.6 1711.16   261.9 1683.59   332.5 1637.57   412.3 1584.72   442.2 1564.14
   452.2 1556.71   462.2 1548.33   472.1 1541.14   482.1 1538.05   487.1 1538.04
   492.1 1538.02   497.1  1538.3     512 1539.58     522 1541.38   591.8 1556.72
   651.5 1565.32   681.3  1568.7     721 1571.42   770.6 1571.76   790.5 1570.88
   830.2 1567.39     850 1566.98     860 1567.89   869.9 1569.58   899.7 1576.37
#Mann= 3 , 0 , 0
       0     .06       0   487.1    .045       0   497.1     .06       0
Bank Sta=487.1,497.1
XS Rating Curve= 0 ,0
Exp/Cntr=0.3,0.1

Type RM Length L Ch R = 1 ,4366.5  ,70.9,70.2,69.5
XS GIS Cut Line= 4
     1770236.881      125437.797     1769917.862      125489.516
     1769610.093      125517.966     1769359.246      125557.087
#Sta/Elev= 30
    10.1 1765.21    40.4 1758.04   131.3 1741.71   141.4 1739.03   151.5 1735.44
   161.6 1730.96   171.7 1725.68   191.9 1713.31   242.4 1677.44   323.2 1625.62
   422.9 1560.08   432.9 1552.54   442.8 1544.16   452.8 1538.32   457.8 1537.61
   462.8 1536.89   467.8 1537.05   502.7 1538.13   512.6 1539.75   562.5 1551.17
   582.4 1554.63   632.3 1556.36   651.8 1557.56   690.9 1560.66   720.1 1564.38
   739.7 1569.21   778.7 1581.56     808 1590.14   847.1 1600.28   886.1 1609.01
#Mann= 3 , 0 , 0
       0     .06       0   457.8    .045       0   467.8     .06       0
Bank Sta=457.8,467.8
XS Rating Curve= 0 ,0
Exp/Cntr=0.3,0.1

Type RM Length L Ch R = 1 ,4296.3  ,134.9,132.3,129.7
XS GIS Cut Line= 4
     1770248.242      125372.471     1769978.419      125406.554
     1769577.944      125457.678     1769362.086      125517.323
#Sta/Elev= 30
    10.1 1728.19    30.2 1725.47    70.5 1723.31   100.7  1718.6     141 1710.61
   201.5 1697.32   211.5 1694.74   221.6 1690.83   231.7 1685.19   282.1 1652.15
   403.2 1579.91   433.5 1559.06   453.6 1541.91   463.7 1535.87   468.8 1535.33
   473.8  1534.8   478.8 1535.07   524.3 1536.15   534.4    1537   594.9 1545.88
   675.7 1551.84   704.9 1555.02   714.6 1556.72   734.1 1562.81   753.6 1570.93
   792.5  1592.3     812 1601.31   821.7  1604.7   841.2 1609.79   899.6 1621.27
#Mann= 3 , 0 , 0
    10.1     .06       0   468.8    .045       0   478.8     .06       0
#XS Ineff= 2 , 0
                          508.25         1554.14
Permanent Ineff=
       F       F
Bank Sta=468.8,478.8
XS Rating Curve= 0 ,0
Exp/Cntr=0.3,0.1

Type RM Length L Ch R = 1 ,4164    ,236.7,235.7,234.8
XS GIS Cut Line= 4
     1770208.478       125244.66     1769907.412      125267.382
     1769654.631      125332.708     1769326.773      125407.024
#Sta/Elev= 30
    10.1 1666.96    30.2 1662.45    80.5 1654.28   171.1 1635.15   211.3 1627.44
   251.6 1618.22   261.7 1614.57   301.9 1594.63   392.3 1565.15   402.3  1561.3
   412.4 1554.35   432.5 1534.68   442.5 1529.25   447.5 1528.72   452.5 1528.19
   457.5 1528.54   522.8 1534.04   572.9 1539.87   642.1  1544.1   661.9 1546.95
   671.8 1549.88   691.5 1558.25   711.3 1568.26   750.9 1592.14   780.5    1612
   810.2 1637.59   820.1 1644.99     830 1650.48   849.7 1657.57   899.2 1668.44
#Mann= 3 , 0 , 0
       0     .06       0   447.5    .045       0   457.5     .06       0
Bank Sta=447.5,457.5
XS Rating Curve= 0 ,0
Exp/Cntr=0.3,0.1

Type RM Length L Ch R = 1 ,3928.2  ,300.1,299.4,298.8
XS GIS Cut Line= 4
     1770145.993      124957.796     1769856.288      125031.642
     1769577.944      125116.849      1769291.08      125227.619
#Sta/Elev= 30
      10 1726.22    39.9 1712.57    79.7 1691.96   109.6 1677.15   139.5 1663.52
   199.3 1640.16   259.1 1620.04     279 1611.68     299 1601.14     309 1594.48
   339.1 1572.86   369.2  1552.6   379.3  1546.5   419.4 1526.71   429.5 1522.82
   434.5 1522.13   439.5 1521.44   444.5 1521.66   499.7 1526.58   509.8 1528.12
   519.8 1530.69   590.1 1552.94   659.5 1573.62   669.4  1575.2   689.3 1576.38
   699.2 1578.33   798.4 1605.71     848 1621.38   877.7 1632.02   897.6 1639.74
#Mann= 3 , 0 , 0
       0     .06       0   434.5    .045       0   444.5     .06       0
Bank Sta=434.5,444.5
XS Rating Curve= 0 ,0
Exp/Cntr=0.3,0.1

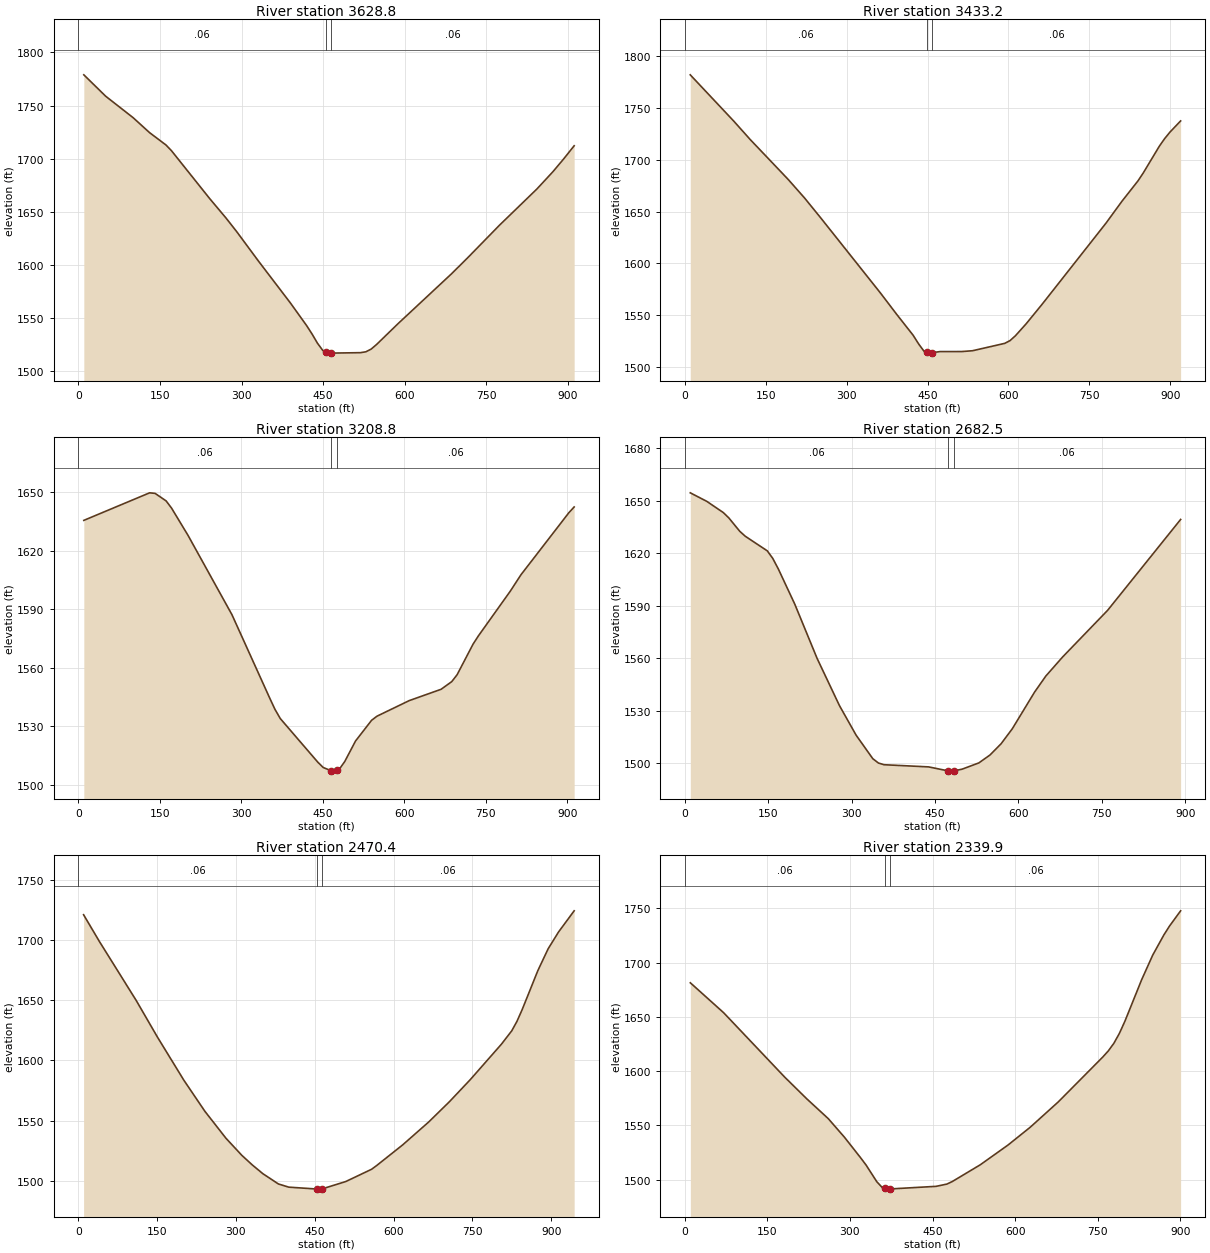
Type RM Length L Ch R = 1 ,3628.8  ,196,195.6,195.3
XS GIS Cut Line= 4
     1770100.549      124687.973     1769840.509       124718.29
     1769467.175      124847.026     1769230.091      124939.218
#Sta/Elev= 30
    10.1 1778.91    50.3 1758.76   100.7 1738.58   130.9 1724.51   161.1 1712.86
   171.2 1707.47   241.7 1662.24   271.7 1643.95   291.4 1631.07   330.9  1603.7
   390.1 1563.93   419.8  1542.7   429.6  1534.9   439.5 1526.28   449.4 1519.42
   454.3 1518.23   459.3 1517.01   464.3 1517.03   518.5 1517.44   528.4 1518.27
   538.2 1520.84   548.1 1525.17   587.6 1544.79   686.1 1591.84   715.4 1606.72
   774.1  1637.5   842.6 1671.44     872  1687.7   891.5 1699.56   911.1 1712.14
#Mann= 3 , 0 , 0
       0     .06       0   454.3    .045       0   464.3     .06       0
Bank Sta=454.3,464.3
XS Rating Curve= 0 ,0
Exp/Cntr=0.3,0.1

Type RM Length L Ch R = 1 ,3433.2  ,214,224.4,230.9
XS GIS Cut Line= 4
     1770046.584      124500.517     1769736.998      124545.961
     1769501.258      124631.168      1769171.79      124764.659
#Sta/Elev= 30
    10.1  1781.9    90.8 1737.23   121.1 1719.55   191.8 1680.88   222.1    1663
   252.3 1643.64     363 1571.17   393.1 1550.59   423.2 1530.67   433.2 1522.46
   443.3 1515.27   448.3 1514.32   453.3 1513.37   458.3 1513.83   473.3 1514.86
   513.4 1514.88   533.5 1515.69   593.2 1522.81   603.1 1525.53   612.9 1530.14
   632.7 1541.63   662.3 1560.48   780.8 1638.82   810.4 1659.95   840.1  1679.6
   849.9 1687.25   879.6 1712.98   889.4 1720.28   899.3  1726.6   919.1 1737.42
#Mann= 3 , 0 , 0
       0     .06       0   448.3    .045       0   458.3     .06       0
Bank Sta=448.3,458.3
XS Rating Curve= 0 ,0
Exp/Cntr=0.3,0.1

Type RM Length L Ch R = 1 ,3208.8  ,525,526.2,527.4
XS GIS Cut Line= 4
     1769960.337      124247.867     1769722.797      124401.108
     1769399.009      124440.872     1769140.547      124599.925
#Sta/Elev= 30
    10.1 1635.45   131.2 1649.55   141.3 1649.26   161.5 1645.43   171.6  1641.7
   201.9 1627.76   282.7 1587.18   351.9 1544.67   361.8 1538.77   371.6 1534.03
   440.8 1511.66   450.7 1508.97   465.5 1507.31   470.5 1507.12   475.5 1507.65
   480.4 1508.17   490.3 1512.05     510 1522.49   539.7 1533.15   549.6 1535.24
   608.9 1543.21   667.6 1549.01   687.2 1552.94     697 1556.45   726.4 1572.12
   736.2 1576.34   794.9 1599.23   814.5 1607.61   902.6 1639.35   912.4 1642.31
#Mann= 3 , 0 , 0
       0     .06       0   465.5    .045       0   475.5     .06       0
Bank Sta=465.5,475.5
XS Rating Curve= 0 ,0
Exp/Cntr=0.3,0.1

Type RM Length L Ch R = 1 ,2682.5  ,197.6,212.2,226.8
XS GIS Cut Line= 4
     1769891.808      123957.099     1769702.915      123898.386
     1769262.678      123929.628     1769026.938      124020.516
#Sta/Elev= 30
     9.9  1654.5    39.6 1649.62    69.2 1643.23    79.1  1640.2    98.9  1632.5
   108.8 1629.68   148.4 1621.33   158.2 1617.03   168.1 1611.08   197.8  1590.9
   237.9 1559.92   278.1 1532.94   308.1 1516.02   338.2 1502.53   348.3 1500.08
   358.3 1499.11   438.5 1497.87   473.7 1495.59   478.7 1495.45   483.7 1495.58
   498.7 1496.56   528.8 1500.13   548.9 1504.66   568.9 1511.09     589 1519.64
   629.1  1540.6   649.3 1549.76   679.6  1560.7   760.4 1587.31   891.8 1639.28
#Mann= 3 , 0 , 0
       0     .06       0   473.7    .045       0   483.7     .06       0
Bank Sta=473.7,483.7
XS Rating Curve= 0 ,0
Exp/Cntr=0.3,0.1

Type RM Length L Ch R = 1 ,2470.4  ,144.3,130.5,116.4
XS GIS Cut Line= 4
     1769887.531      123813.178     1769538.181      123776.255
     1769373.447      123651.285     1769004.216      123762.054
#Sta/Elev= 30
      10 1721.01    40.1  1698.8   110.4 1649.66   150.6 1619.39   200.7 1583.72
   240.9  1557.8     281 1535.43   311.1 1521.29   331.2 1513.24   351.3 1505.99
   380.8 1497.49   400.5 1494.85   454.6 1493.27   459.6 1493.21   464.6  1493.5
   508.8 1499.48   558.1 1509.69     568 1512.87   617.4 1529.99   666.8 1548.95
   706.3 1565.81   745.9  1584.1   805.2 1613.54   824.9 1624.68   834.8 1632.54
   844.7 1642.28   874.4  1674.5   894.1 1692.73   913.9 1706.69   943.6 1724.25
#Mann= 3 , 0 , 0
       0     .06       0   454.6    .045       0   464.6     .06       0
Bank Sta=454.6,464.6
XS Rating Curve= 0 ,0
Exp/Cntr=0.3,0.1

Type RM Length L Ch R = 1 ,2339.9  ,95,85.5,76.1
XS GIS Cut Line= 4
     1769890.371      123659.805     1769683.033      123617.202
     1769418.891      123628.563     1769004.216       123719.45
#Sta/Elev= 30
    10.1  1681.3    70.6 1653.72   181.4 1594.44   221.5 1574.43   260.6 1556.16
     290 1539.02   319.4 1520.06   329.2 1513.44   348.8 1498.01   358.6 1492.67
   363.3 1491.96   368.3  1491.2   373.3 1491.37   456.5 1493.77   476.1 1495.85
   486.2 1498.29   536.7 1513.63   587.2 1531.86   627.7 1548.35   678.2 1571.47
   759.1 1612.85   769.2 1618.52   779.3 1625.52   789.4 1634.72   799.5 1646.01
   829.8 1684.12     850 1706.88   870.3 1725.52   880.4 1733.57   900.6 1747.62
#Mann= 3 , 0 , 0
       0     .06       0   363.3    .045       0   373.3     .06       0
Bank Sta=363.3,373.3
XS Rating Curve= 0 ,0
Exp/Cntr=0.3,0.1

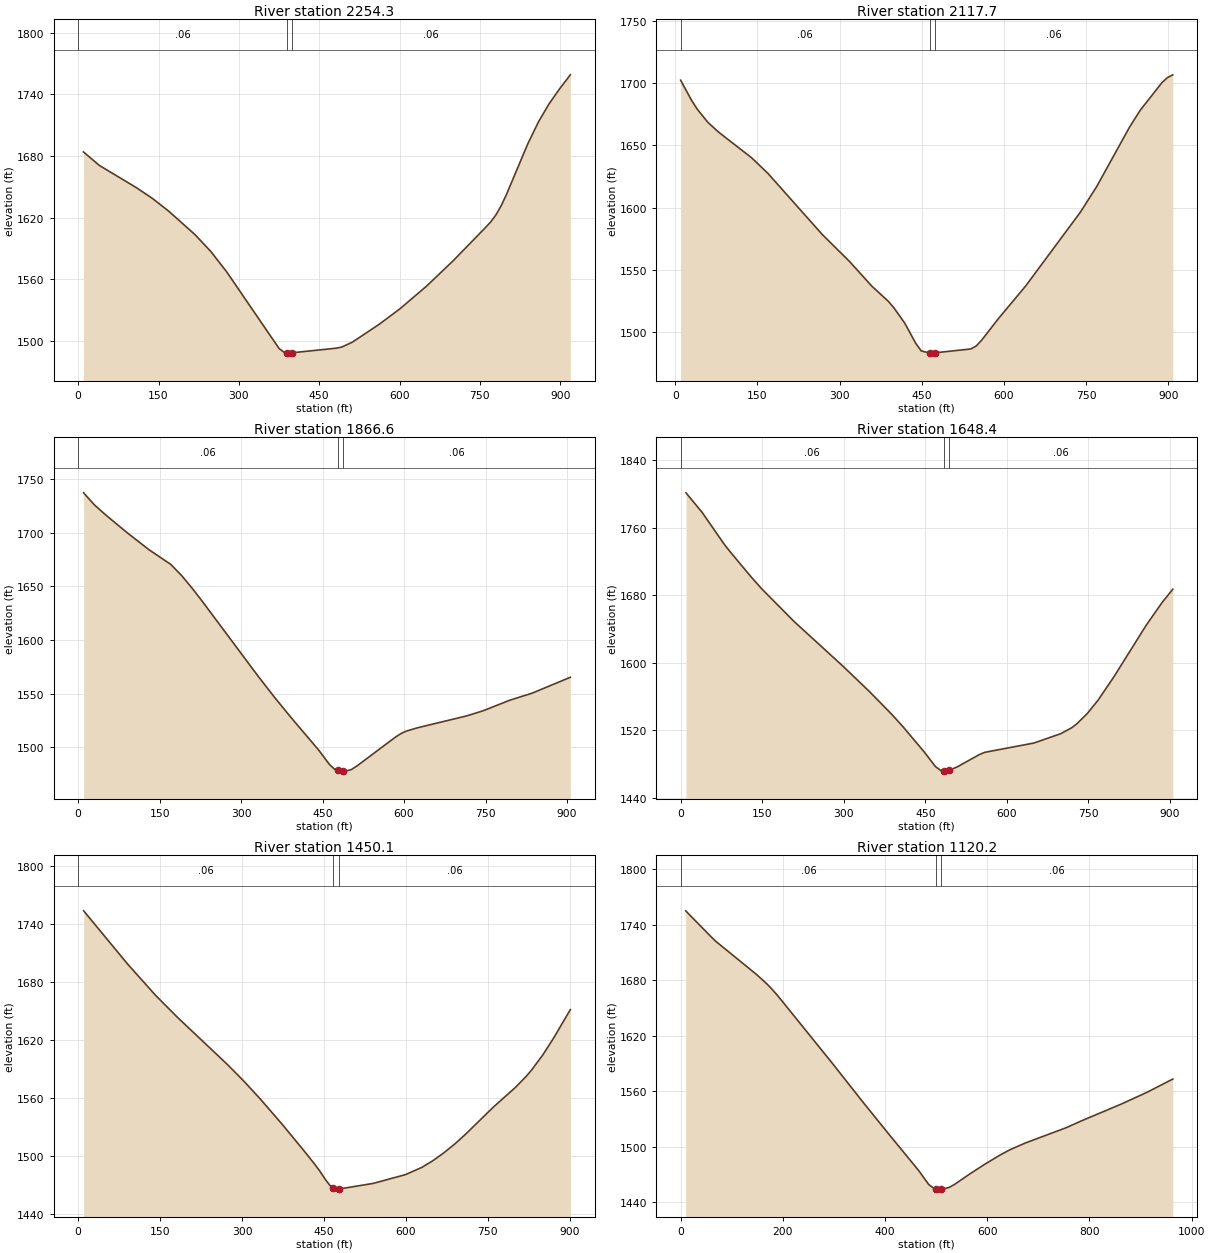
Type RM Length L Ch R = 1 ,2254.3  ,134,136.6,139.3
XS GIS Cut Line= 4
      1769879.01       123475.19     1769592.146      123489.391
      1769404.69       123594.48     1768995.695      123674.007
#Sta/Elev= 30
     9.9 1684.02    39.6 1670.87   108.9 1649.16   138.7 1638.72   168.4 1626.63
   217.9 1603.62   247.6 1587.14   277.3 1567.24   375.1 1492.61   384.9 1488.75
   389.7 1488.44   394.7 1488.12   399.7 1488.47   482.6 1492.98   492.4 1494.08
     512 1498.84   561.6 1516.05   601.3 1531.51   650.9 1553.59   700.5 1578.28
     760 1610.18     770 1615.79   779.9  1622.7   789.8 1631.74   799.7 1642.72
   839.4 1691.92   859.3 1713.25   879.1 1730.84   898.9 1745.56   918.8 1759.08
#Mann= 3 , 0 , 0
       0     .06       0   389.7    .045       0   399.7     .06       0
Bank Sta=389.7,399.7
XS Rating Curve= 0 ,0
Exp/Cntr=0.3,0.1

Type RM Length L Ch R = 1 ,2117.7  ,244.3,251.1,257.9
XS GIS Cut Line= 4
      1769873.33       123367.26     1769575.104       123367.26
     1769248.476      123497.911     1768992.992      123534.254
#Sta/Elev= 30
     9.9 1702.39    29.8 1686.26    39.8 1679.38    59.6 1668.55    79.5 1660.58
   139.2 1640.18     169 1627.66   268.4 1578.49   318.3 1556.77   358.5 1537.19
   388.7 1524.94   398.7 1519.87   418.8 1507.45   438.9 1491.17     449 1485.03
   464.1 1483.32  469.16 1483.24   474.1 1483.49   539.5 1486.59   549.5 1489.03
   559.6 1493.81   589.7 1510.86     640 1537.37   739.3 1596.33   769.1 1616.87
   828.7 1664.34   848.5 1678.16   888.2 1700.38   898.1 1704.39   908.1 1706.68
#Mann= 3 , 0 , 0
     9.9     .06       0   464.1    .045       0   474.1     .06       0
Bank Sta=464.1,474.1
XS Rating Curve= 0 ,0
Exp/Cntr=0.3,0.1

Type RM Length L Ch R = 1 ,1866.6  ,221.8,218.2,214.6
XS GIS Cut Line= 4
     1769844.927      123120.159     1769498.418      123179.804
     1769205.873      123191.165     1768967.292      123299.094
#Sta/Elev= 30
      10 1737.03    30.1 1725.75    50.2 1716.65    90.4  1699.8   130.6 1683.97
   170.8 1670.25   190.9 1659.73     211 1647.47   231.1 1634.23   331.5 1566.11
   361.7 1546.43     392  1527.7   442.5 1497.58   462.7 1483.97   472.7 1479.27
   477.8 1478.51   482.8 1477.76   487.8 1477.78   492.9 1477.81     503 1479.23
   513.1 1482.49   583.8 1509.31   593.9 1512.62     604    1515   624.2 1518.05
   714.9 1529.16   745.1 1533.88   795.4 1543.95   835.7 1550.35   906.2  1565.2
#Mann= 3 , 0 , 0
       0     .06       0   477.8    .045       0   487.8     .06       0
Bank Sta=477.8,487.8
XS Rating Curve= 0 ,0
Exp/Cntr=0.3,0.1

Type RM Length L Ch R = 1 ,1648.4  ,199.5,198.3,197.1
XS GIS Cut Line= 4
     1769830.726      122952.585     1769493.535      122935.591
     1769188.831      123003.709      1768947.34      123086.512
#Sta/Elev= 30
     9.9 1801.26    39.7 1777.99    79.4 1741.04    89.4 1732.74   129.1 1702.03
   148.9 1687.65   208.5 1648.85   297.9  1596.2   347.7 1565.44     388 1538.87
   408.1 1524.68   448.4 1493.81   468.6 1476.81   478.6 1472.03   483.7 1471.71
   488.7  1471.4   493.7 1472.32   508.8 1476.46   549.1 1490.93   559.2 1493.67
   649.8 1504.71   698.9 1515.75   718.6 1522.59   728.4 1527.37     748 1539.76
   767.7 1555.48   797.1 1583.49     856 1644.14   885.5 1671.35   905.1 1687.02
#Mann= 3 , 0 , 0
       0     .06       0   483.7    .045       0   493.7     .06       0
Bank Sta=483.7,493.7
XS Rating Curve= 0 ,0
Exp/Cntr=0.3,0.1

Type RM Length L Ch R = 1 ,1450.1  ,316.6,329.9,343.2
XS GIS Cut Line= 4
     1769782.442      122762.289     1769399.009      122748.088
     1769211.553      122802.052      1768933.21      122963.946
#Sta/Elev= 30
    10.1 1753.72    90.9 1698.42   141.4  1666.5   181.8 1643.52   272.6 1595.08
   302.9 1577.79   333.2  1559.2   373.6  1532.8     413 1505.77   432.5 1491.95
   442.2 1484.57     452  1476.2   461.7 1469.06   466.5  1467.5   471.5 1465.86
   476.5 1465.89   539.8 1471.75   598.9 1480.82   629.1 1488.36   649.2 1495.27
   669.3 1503.39   689.5 1512.64   709.6 1522.95   759.9  1550.7   800.1 1570.95
   820.3 1582.68   830.3 1589.35   850.5 1604.73   870.6 1622.47   900.8 1651.54
#Mann= 3 , 0 , 0
       0     .06       0   466.5    .045       0   476.5     .06       0
Bank Sta=466.5,476.5
XS Rating Curve= 0 ,0
Exp/Cntr=0.3,0.1

Type RM Length L Ch R = 1 ,1120.2  ,456.4,462.1,467.9
XS GIS Cut Line= 4
      1769759.72      122696.963     1769516.398      122527.886
     1769183.151      122395.898     1768883.545      122323.046
#Sta/Elev= 30
     9.9 1754.83    59.3 1726.96    69.1 1721.75   148.1 1686.21   167.9 1676.34
   177.8 1670.68   187.7 1664.54   197.5 1658.01   296.3  1590.4     356 1548.58
   405.8 1514.48   465.6 1474.19   485.5 1458.97   495.4  1454.8   500.4 1454.36
   505.4 1453.93   510.4 1454.12   515.3 1454.31   525.3 1455.81   535.3 1458.75
   565.1 1470.05     595 1480.77   624.9 1490.72   644.8 1496.61   674.6 1503.82
   754.2 1520.27     784 1527.66   863.6  1546.2   913.3 1558.79   963.1 1572.95
#Mann= 3 , 0 , 0
       0     .06       0   500.4    .045       0   510.4     .06       0
Bank Sta=500.4,510.4
XS Rating Curve= 0 ,0
Exp/Cntr=0.3,0.1

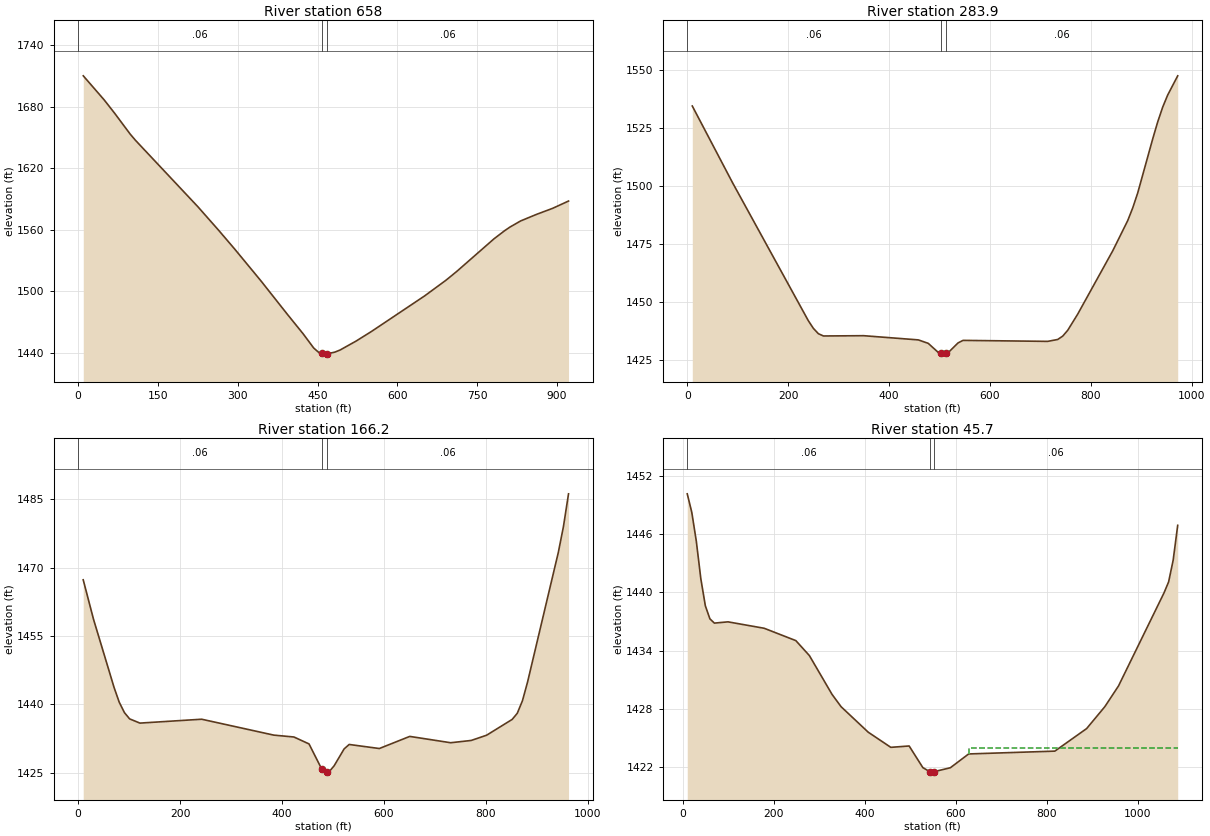
Type RM Length L Ch R = 1 ,658     ,374.4,374.1,373.8
XS GIS Cut Line= 4
     1769825.046      122407.258     1769713.504      122189.525
     1769424.571      121964.181     1769185.019      121766.734
#Sta/Elev= 30
     9.8 1709.93    48.9 1686.59    68.5 1673.64    97.9 1653.18   107.6 1647.25
   225.1  1582.4   264.4 1559.29   294.2  1541.2   343.7  1510.1   393.2 1477.62
   422.9 1458.58   442.7 1444.77   452.6 1440.26   457.5 1439.53   462.5 1438.79
   467.5 1439.08   482.3 1440.71   492.2 1442.77   521.9 1451.36   551.6 1460.98
   651.1  1495.5   691.2 1510.76   711.2 1519.23   781.3 1551.05   801.3 1558.99
   811.3 1562.53   831.4 1568.52   861.4 1574.95   891.5  1580.8   921.5 1587.92
#Mann= 3 , 0 , 0
       0     .06       0   457.5    .045       0   467.5     .06       0
Bank Sta=457.5,467.5
XS Rating Curve= 0 ,0
Exp/Cntr=0.3,0.1

Type RM Length L Ch R = 1 ,283.9   ,118.3,117.7,117
XS GIS Cut Line= 4
     1770049.425      122168.678     1769904.544      121861.128
     1769668.832      121682.997     1769339.364      121611.991
#Sta/Elev= 30
      10 1534.67      90 1501.51     240 1442.09     250 1438.78     260 1436.46
     270 1435.48   349.8  1435.6   458.1 1433.79   477.8  1432.3   497.5 1428.41
   502.4 1428.03   507.4 1427.65   512.4 1427.96   517.2 1428.25   536.9 1432.49
   546.8 1433.58   714.7 1433.15   734.5 1433.97   744.5 1435.43   754.4 1437.95
   774.2 1444.93   843.6 1472.22   873.3 1485.25   883.2 1490.71   893.1 1497.18
   922.9 1520.54   932.8 1527.86   942.7 1534.23   952.6 1539.44   972.4 1547.69
#Mann= 3 , 0 , 0
       0     .06       0   502.4    .045       0   512.4     .06       0
Bank Sta=502.4,512.4
XS Rating Curve= 0 ,0
Exp/Cntr=0.3,0.1

Type RM Length L Ch R = 1 ,166.2   ,118.5,120.6,122.6
XS GIS Cut Line= 4
      1770109.07      122057.909     1769921.614       121722.76
     1769728.477      121586.429     1769387.648      121563.707
#Sta/Elev= 30
    10.1 1467.34    30.3 1458.68    70.7 1443.69    80.8 1440.46    90.9  1438.2
   101.1 1436.82   121.3 1435.89   242.5 1436.74     384 1433.25   423.4 1432.84
     453 1431.32   477.5 1425.89   482.5 1425.13   487.5 1425.17   492.4 1425.21
   502.2 1426.51   521.9 1430.23   531.8  1431.2   590.9 1430.31   650.6 1432.97
   730.9 1431.58   771.1 1432.08   801.3 1433.23   851.5  1436.7   861.5 1438.05
   871.6 1440.79   881.6 1444.88   941.9 1473.31     952    1479     962 1486.21
#Mann= 3 , 0 , 0
       0     .06       0   477.5    .045       0   487.5     .06       0
Bank Sta=477.5,487.5
XS Rating Curve= 0 ,0
Exp/Cntr=0.3,0.1

Type RM Length L Ch R = 1 ,45.7    ,46.9,45.7,44.5
XS GIS Cut Line= 5
     1770188.596      122055.069      1769995.46      121640.393
     1769836.406      121501.221     1769657.653      121490.606
     1769417.379      121492.117
#Sta/Elev= 30
     9.9 1450.12    19.9 1448.21    29.8 1445.26    39.8 1441.37    49.7  1438.6
    59.7 1437.26    69.6 1436.82    99.4 1436.95     179 1436.29   248.6 1435.02
   278.4 1433.48   328.2 1429.49   348.1 1428.22   407.7  1425.6   457.4 1424.04
   497.7 1424.18   527.9 1421.95     543 1421.54     548 1421.49     553 1421.54
   588.3 1421.94   628.5 1423.36     818 1423.65   887.9 1425.97     928 1428.23
     958 1430.36  1058.1 1439.94  1068.1 1441.06  1078.1 1443.29  1088.1 1446.88
#Mann= 3 , 0 , 0
     9.9     .06       0     543    .045       0     553     .06       0
#XS Ineff= 2 , 0
                           628.6         1423.94
Permanent Ineff=
       F       F
Bank Sta=543,553
XS Rating Curve= 0 ,0
Exp/Cntr=0.3,0.1

Chan Stop Cuts=-1
Use User Specified Reach Order=0